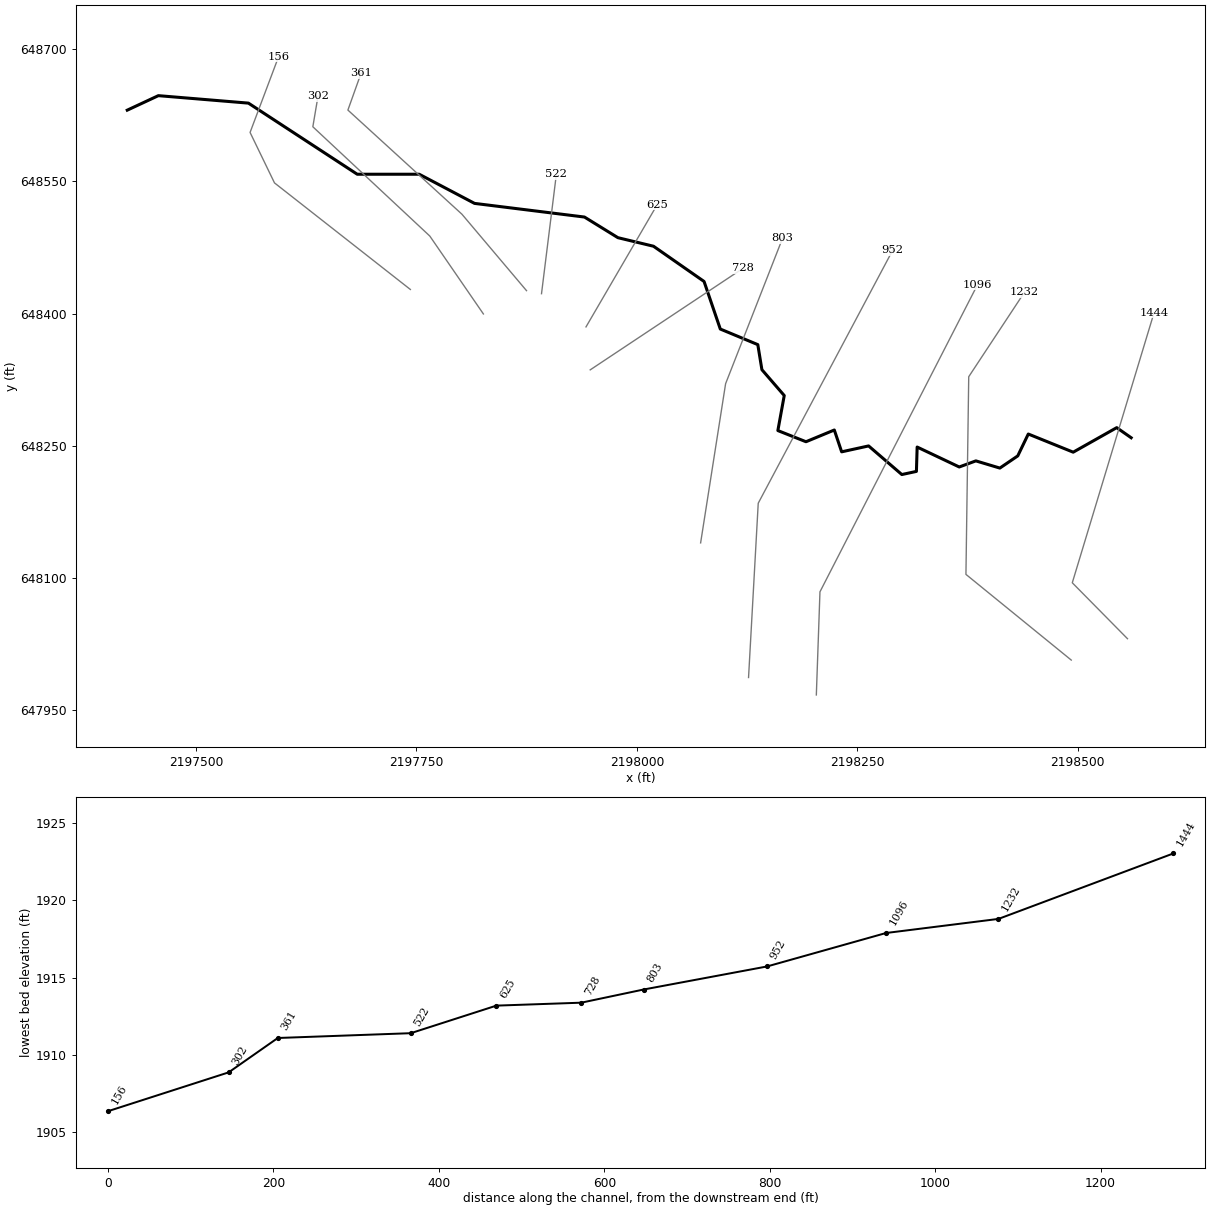
--- SROCKLKRN.prj (project) ---

Proj Title=SROCKLKRN
Current Plan=p01
Default Exp/Contr=0,0
English Units
Geom File=g01
Flow File=f01
Plan File=p01
BEGIN DESCRIPTION:
---------- MODELED AS PART OF WVEMD CTP PROGRAM, 2023----------
Stream Name: Smooth Rock Lick Run
Flood Zone:  AFH
Upshur County, WV
HEC-RAS Version: RAS 6.3
Vertical Datum: NAVD88
Projection: NAD 1983 StatePlane West Virginia S FIPS 4702 (US Feet)
Terrain: 1-meter LIDAR (FEMA Region III 3DEP collected 2016-2018)
Land Use: 2019 NLCD
Hydrologic Method:
WV 2010 Regional Regression Equations
Additional Model Notes:
None
END DESCRIPTION:
DSS Export Rating Curves= 0
DSS Export Rating Curve Sorted= 0
DSS Export Volume Flow Curves= 0
DXF OffsetX= 0
DXF OffsetY= 0
DXF ScaleX= 0
DXF ScaleY= 0

--- SROCKLKRN.p01 (plan) ---

Plan Title=Floodplain
Program Version=6.31
Short Identifier=Floodplain
Geom File=g01
Flow File=f01
Subcritical Flow
K Sum by GR= 0
Std Step Tol= 0.01
Critical Tol= 0.01
Num of Std Step Trials= 20
Max Error Tol= 0.3
Flow Tol Ratio= 0.001
Split Flow NTrial= 30
Split Flow Tol= 0.02
Split Flow Ratio= 0.02
Log Output Level= 0
Friction Slope Method= 1
Unsteady Friction Slope Method= 2
Unsteady Bridges Friction Slope Method= 1
Parabolic Critical Depth
Global Vel Dist= 0 , 0 , 0
Global Log Level= 0
CheckData=True
Encroach Param=-1 ,0,0, 0
Mapping Interval=1HOUR
Computation Time Step Use Courant=        0
Computation Time Step Use Time Series=    0
Computation Time Step Count To Double=0
Computation Time Step Max Doubling=0
Computation Time Step Max Halving=0
Computation Time Step Residence Courant=0
Run HTab= 0
Run UNet= 0
Run Sediment= 0
Run PostProcess= 0
Run WQNet= 0
Run RASMapper=-1
UNET Theta= 0
UNET Theta Warmup= 0
UNET ZTol= 0
UNET ZSATol= 0
UNET MxIter= 0
UNET Max Iter WO Improvement= 0
UNET MaxInSteps= 0
UNET DtIC= 0
UNET DtMin= 0
UNET MaxCRTS= 0
UNET WFStab= 0
UNET SFStab= 0
UNET WFX= 1
UNET SFX= 1
UNET Gravity=32.17405
UNET 1D Methodology=Finite Difference
UNET DSS MLevel= 1
UNET Pardiso=0
UNET DZMax Abort= 0
UNET Use Existing IB Tables= 0
UNET Froude Reduction=False
UNET Froude Limit= 0
UNET Froude Power= 0
UNET D1 Cores= 0
UNET WindReference=Eulerian
UNET WindDragFormulation=Hsu (1988)
UNET D2 Coriolis=0
UNET D2 Cores= 0
UNET D2 Theta= 1
UNET D2 Theta Warmup= 1
UNET D2 Z Tol= 0.01
UNET D2 Volume Tol= 0.01
UNET D2 Max Iterations= 20
UNET D2 Equation= 0
UNET D2 RampUpFraction=0.1
UNET D2 TimeSlices= 1
UNET D2 Turbulence Formulation=Non-Conservative (original)
UNET D2 Eddy Viscosity=0.3
UNET D2 Transverse Eddy Viscosity=0.1
UNET D2 Smagorinsky Mixing=0
UNET D2 BCVolumeCheck=0
UNET D2 Cores=0
UNET D2 SolverType=PARDISO (Direct)
UNET D2 Minimum Iterations= 3
UNET D2 Maximum Iterations= 30
UNET D2 Restart Number= 10
UNET D2 Relaxation Coeff=1.3
UNET D2 SOR Precondition Iterations= 10
UNET D2 ILUT Maximum Fill= 8
UNET D2 ILUT Tolerance=1E-08
UNET D2 Convergence Tolerance=0.00001
UNET D1D2 MaxIter= 0
UNET D1D2 ZTol=0.01
UNET D1D2 QTol=0.1
UNET D1D2 MinQTol=1
Write IC File= 0
Write IC File at Fixed DateTime=0
Write IC File at Sim End=0
Echo Input=False
Echo Parameters=False
Echo Output=False
Write Detailed= 0
HDF Write Warmup=0
HDF Write Time Slices=0
HDF Flush=0
HDF Compression= 1
HDF Chunk Size= 1
HDF Spatial Parts= 1
HDF Use Max Rows=0
HDF Fixed Rows= 1
Calibration Method= 0
Calibration Iterations= 20
Calibration Max Change=0.05
Calibration Tolerance=0.2
Calibration Maximum=1.5
Calibration Minimum=0.5
Calibration Optimization Method= 1
WQ AD Non Conservative
WQ ULTIMATE=-1
WQ Max Comp Step=1HOUR
WQ Output Interval=15MIN
WQ Output Selected Increments= 0
WQ Create Restart=0
WQ Fixed Restart=0
WQ System Summary=0
WQ Write To DSS=0
Sorting and Armoring Iterations= 10
XS Update Threshold= 0.02
Bed Roughness Predictor= 0
Hydraulics Update Threshold= 0.02
Energy Slope Method= 1
Volume Change Method= 1
Sediment Retention Method= 0
Sediment TS Multiplier= 1
Warm Up Method= 0
XS Weighting Method= 0
Number of US Weighted Cross Sections= 1
Number of DS Weighted Cross Sections= 1
Upstream XS Weight=0
Main XS Weight=1
Downstream XS Weight=0
Number of DS XS's Weighted with US Boundary= 1
Upstream Boundary Weight= 1
Weight of XSs Associated with US Boundary= 0
Number of US XS's Weighted with DS Boundary= 1
Downstream Boundary Weight= 0.5
Weight of XSs Associated with DS Boundary= 0.5
Percentile Method= 0
Sediment Output Level= 3
Mass or Volume Output= 0
Output Increment Type= 1
Profile and TS Output Increment= 1
Transport Output Increment 1
XS Output Flag= 0
XS Output Increment= 10
Read HDF5 Sediment Hotstart= 0
Sediment Hotstart Type= 0
Write Gradation File= 0
Read Gradation Hotstart= 0
Write HDF5 File= 1
Write Binary Output= 1
Write DSS Sediment File= 0
DSS Sediment Output Type= 1
SV Curve= 0
Specific Gage Flag= 0
Subcell Erosion Methods= 0
Subcell Deposition Methods= 0
Advection Scheme= 1
Matrix Solver= 0
Implicit Weighting Factor= 1
Maximum Outer Loop Convergence Iterations= 5
Convergence Maximum Absolute= 0.001
Convergence RMSE= 0.0001
Grain Fractions Max Abs Error= 0.001
Max Subgrid Regions= 1
Max Subgrid Length Scale= 3.402823E+38
Initial Layer Thickness= 3.402823E+38
Min Layer Thickness= 3.402823E+38
Max Layer Thickness= 3.402823E+38
Number of Layers= 5

--- SROCKLKRN.f01 (steady flow) ---

Flow Title=Flows
Program Version=6.31
Number of Profiles= 1
Profile Names=01pct
River Rch & RM=SROCKLKRN,Main            ,1444
     316
Boundary for River Rch & Prof#=SROCKLKRN,Main            , 1
Up Type= 0
Dn Type= 3
Dn Slope=0.02019
DSS Import GetInterval= 0
DSS Import GetPeak= 0
DSS Import FillOption= 0

--- SROCKLKRN.g01 (geometry) ---

Geom Title=Geometry
Program Version=6.31

River Reach=SROCKLKRN       ,Main
Reach XY= 30
2198560.75460054648259.1114483922198544.37429976648270.565659731
2198495.01579773648242.735306248 2198444.0593958648263.337467548
2198432.11230502648238.5198877722198411.79966411648224.698915604
2198384.57653711648232.8658537032198365.72975688 648225.95536762
2198317.98458031648248.5715038932198317.14694563648220.929559559
2198300.60366076648217.3696121822198262.91010031648249.827955908
 2198232.3364346648243.1268784942198224.00657848648267.887082944
2198191.87420819648254.5810374232198159.97061356648267.258856937
2198167.21033848648306.9965226012198141.87188951648336.313736289
2198137.22253658648364.740656669 2198094.6778338648382.424917253
     2198076.257      648436.383      2198018.91       648476.36
     2197978.532      648486.061     2197940.586      648509.469
     2197815.905      648524.951     2197753.121      648558.031
      2197682.81      648558.031     2197559.388      648638.701
     2197457.227      648647.171     2197421.943      648630.717

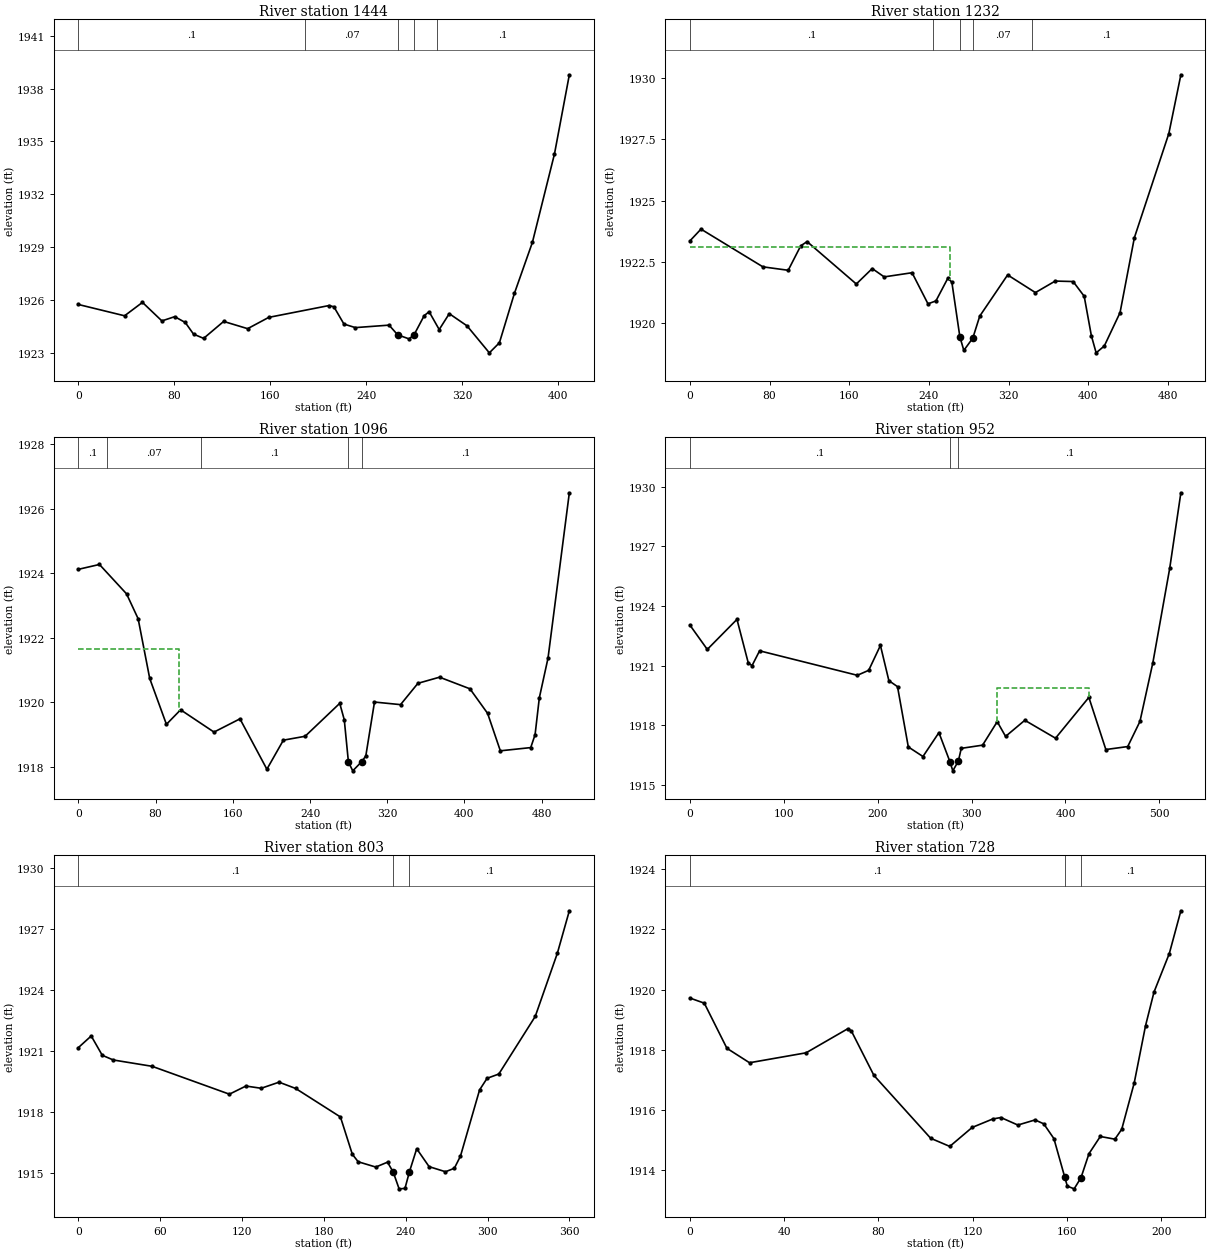
Type RM Length L Ch R = 1 ,1444    ,211.5,211.5,211.5
XS GIS Cut Line= 3
2198556.57688028648031.1560802582198493.96516144648094.591637512
2198586.74367966648401.018400898
#Sta/Elev= 30
       0 1925.76    38.5 1925.12    53.4 1925.88    69.6 1924.83    80.3 1925.07
    89.1 1924.74      96 1924.08   104.4 1923.84   121.1  1924.8   141.1 1924.39
   158.7 1925.03   208.9  1925.7     213 1925.63   221.4 1924.65   230.9 1924.45
     259 1924.59   266.2 1924.04   275.7 1923.81   279.9 1924.05   288.3 1925.13
   292.4 1925.35   300.8 1924.34   309.2 1925.24     324 1924.55   342.6 1923.02
     351 1923.59   363.5 1926.39   378.5 1929.28   396.9 1934.29   409.3 1938.78
#Mann= 5 ,-1,0
       0      .1       0  189.13     .07       0   266.2    .045       0
   279.9     .07       0  299.13      .1       0
Bank Sta=266.2,279.9
XS Rating Curve= 0 ,0
Exp/Cntr(USF)=0,0
Exp/Cntr=0.3,0.1

Type RM Length L Ch R = 1 ,1232    ,135.9,135.9,135.9
XS GIS Cut Line= 4
2198492.78624867648006.9031014262198373.32967982648104.116033322
2198376.49125654648328.3306946312198439.75639886648424.216925955
#Sta/Elev= 30
       0 1923.36    11.1 1923.84    73.3  1922.3    98.7 1922.16   111.3 1923.16
   117.7 1923.33   167.1  1921.6   183.1 1922.23   195.1 1921.89   223.1 1922.06
   239.1 1920.79   247.1 1920.91   259.1 1921.84   263.1 1921.67   271.1 1919.45
   275.1 1918.89   284.1 1919.39   291.1 1920.29   319.1 1921.97     347 1921.25
   366.9 1921.72   384.9  1921.7     396  1921.1   403.2 1919.49     408 1918.79
   416.2 1919.07     432 1920.43   446.4 1923.49     481 1927.74   493.1 1930.14
#Mann= 5 ,-1,0
       0      .1       0  244.01     .07       0   271.1    .045       0
   284.1     .07       0  344.01      .1       0
#XS Ineff= 2 , 0
          261.13 1923.09
Permanent Ineff=
       F       F
Bank Sta=271.1,284.1
XS Rating Curve= 0 ,0
Exp/Cntr(USF)=0,0
Exp/Cntr=0.3,0.1

Type RM Length L Ch R = 1 ,1096    ,143.8,143.8,143.8
XS GIS Cut Line= 3
 2198203.6189682647967.3588579442198207.73816023648084.343911581
2198386.51109431648432.827557276
#Sta/Elev= 30
       0 1924.12    21.8 1924.27    49.9 1923.36    61.9 1922.59    73.9 1920.74
    91.2 1919.32   105.9 1919.77   140.5 1919.08   167.4 1919.49   195.3 1917.93
   212.4 1918.83   234.9 1918.95   270.8 1919.97   275.5 1919.46   279.8 1918.15
   284.3 1917.88   293.4 1918.16   297.8 1918.34   306.8 1920.01   333.8 1919.93
   351.8 1920.59   374.2 1920.78   405.7 1920.42     424 1919.66   437.2  1918.5
   468.7  1918.6   473.2    1919   477.6 1920.14   486.6 1921.37   508.7 1926.49
#Mann= 5 ,-1,0
       0      .1       0      30     .07       0  127.06      .1       0
   279.8    .045       0   293.4      .1       0
#XS Ineff= 2 , 0
          104.45 1921.66
Permanent Ineff=
       F       F
Bank Sta=279.8,293.4
XS Rating Curve= 0 ,0
Exp/Cntr(USF)=0,0
Exp/Cntr=0.3,0.1

Type RM Length L Ch R = 1 ,952     ,149.3,149.3,149.3
XS GIS Cut Line= 3
2198126.72074659647987.1123568632198137.71189573648184.852197101
2198290.16216839648471.670194612
#Sta/Elev= 30
       0 1923.04    18.5 1921.82    50.1 1923.33    62.2 1921.13    66.2 1921.01
    74.2 1921.75   178.3 1920.52   190.4 1920.77   202.9 1922.02   211.9 1920.25
   221.1 1919.95   232.6 1916.92   248.2 1916.44   265.2 1917.64     277 1916.17
     280 1915.72   285.9 1916.21     289 1916.85   311.7 1917.01   327.3 1918.19
   336.2 1917.45   356.7 1918.26   389.4 1917.36   424.9 1919.41     443 1916.79
   466.3 1916.94   479.3  1918.2   493.1 1921.16     511 1925.89   522.9 1929.69
#Mann= 3 ,-1,0
       0      .1       0     277    .045       0   285.9      .1       0
#XS Ineff= 1 ,-1
  327.55  425.24  1919.9
Permanent Ineff=
       F
Bank Sta=277,285.9
XS Rating Curve= 0 ,0
Exp/Cntr(USF)=0,0
Exp/Cntr=0.3,0.1

Type RM Length L Ch R = 1 ,803     ,75.3,75.3,75.3
XS GIS Cut Line= 3
2198072.35623564648139.8487324962198100.69477675648320.422551842
2198165.27867819648485.343000283
#Sta/Elev= 30
       0 1921.17     9.4 1921.74    17.5 1920.79    25.6 1920.56      54 1920.25
   110.7 1918.88   122.8 1919.28     134 1919.17   147.1 1919.47   159.3 1919.16
   192.1 1917.76   200.8 1915.93   205.1 1915.56     218  1915.3   226.6 1915.54
230.8023 1915.05   235.1 1914.23   239.4 1914.25242.70231915.074     248  1916.2
   257.1 1915.32   269.1 1915.07   275.6 1915.24   280.1 1915.84   294.1 1919.09
   299.6 1919.66   308.2 1919.87   334.9  1922.7   351.1  1925.8   359.9 1927.89
#Mann= 3 ,-1,0
       0      .1       0230.8023    .045       0242.7023      .1       0
Bank Sta=230.8023,242.7023
XS Rating Curve= 0 ,0
Exp/Cntr(USF)=0,0
Exp/Cntr=0.3,0.1

Type RM Length L Ch R = 1 ,728     ,102.6,102.6,102.6
XS GIS Cut Line= 2
2197947.09507369648336.1088959922198120.63060464648451.451350654
#Sta/Elev= 30
       0 1919.72     6.1 1919.55    15.7 1918.05    25.3 1917.57    49.3  1917.9
      67  1918.7    68.5 1918.63    78.1 1917.15   102.2 1915.06   110.3 1914.79
   119.8 1915.42   128.5  1915.7     132 1915.75   139.2  1915.5   146.5 1915.67
   150.2 1915.54   154.5 1915.05  159.14 1913.76   160.2 1913.47   163.1 1913.38
     166 1913.75   169.4 1914.55   174.2 1915.12   180.4 1915.03   183.3 1915.36
   188.6  1916.9   193.4  1918.8     197 1919.92   203.5  1921.2   208.4 1922.62
#Mann= 3 ,-1,0
       0      .1       0  159.14    .045       0     166      .1       0
Bank Sta=159.14,166
XS Rating Curve= 0 ,0
Exp/Cntr(USF)=0,0
Exp/Cntr=0.3,0.1

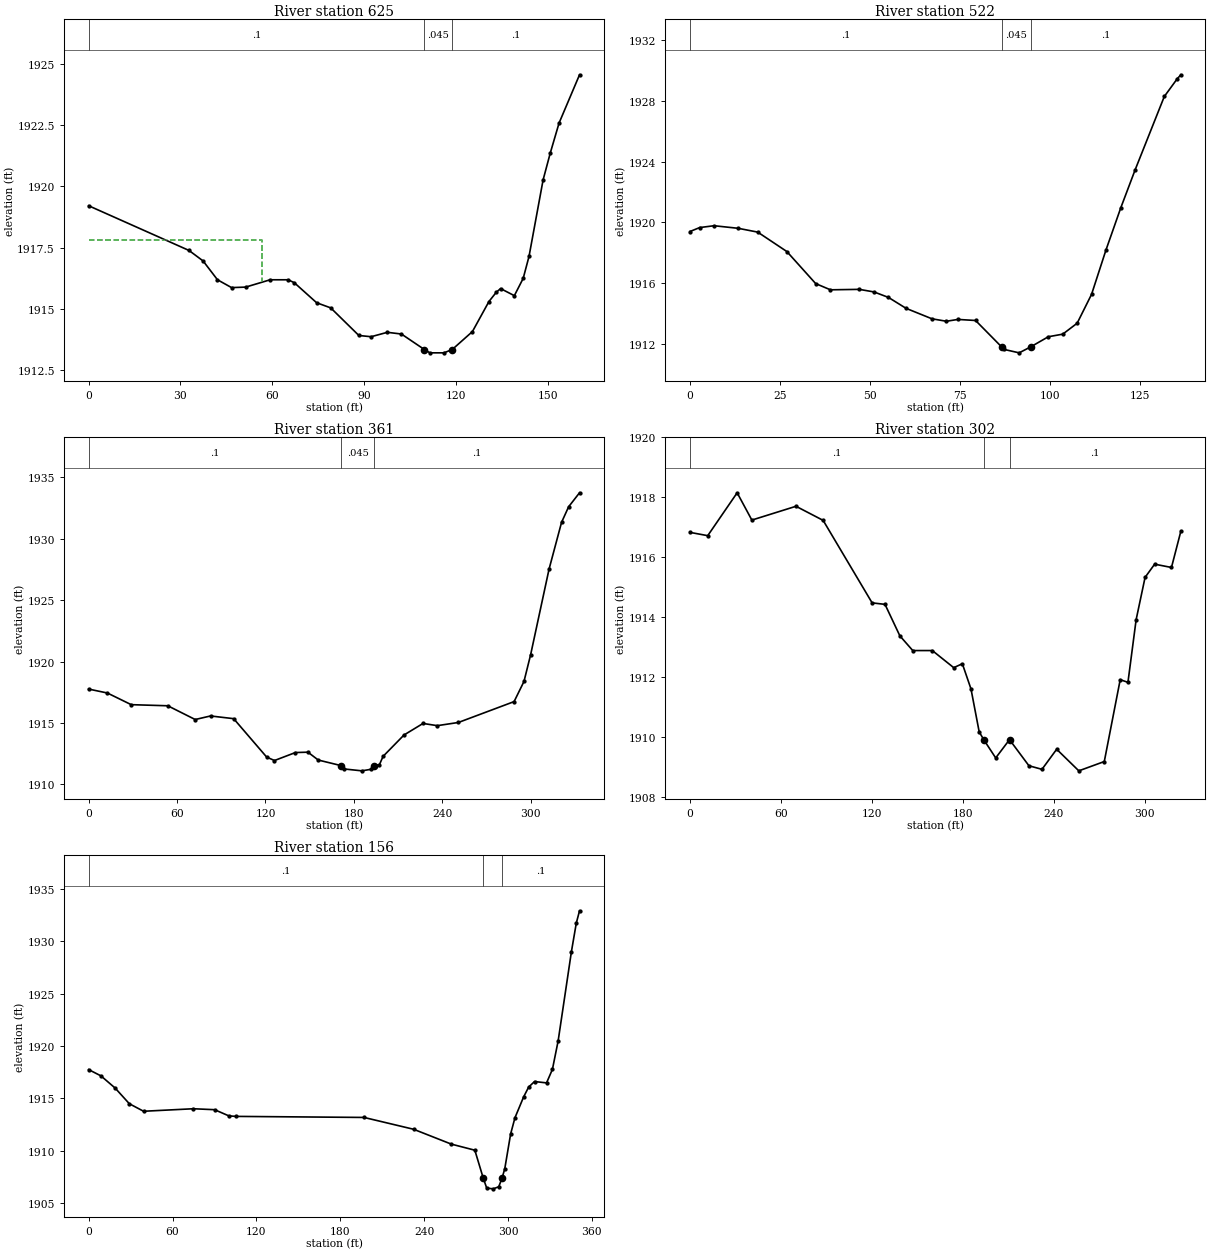
Type RM Length L Ch R = 1 ,625     ,99.3,103.5,106.9
XS GIS Cut Line= 2
2197942.32702941648384.8398263222198023.06827102648523.445624426
#Sta/Elev= 30
       0 1919.21    32.8 1917.38    37.4 1916.95    42.1 1916.18    46.7 1915.86
    51.3 1915.88    59.3 1916.18    65.2 1916.18    67.2 1916.06    74.5 1915.24
    79.1 1915.03    88.3  1913.9    92.3 1913.85    97.6 1914.03   102.2 1913.96
   109.71913.326   111.5 1913.19   116.1 1913.19   118.81913.326   125.4 1914.06
   130.8 1915.29   133.2 1915.67   134.6 1915.82   139.1 1915.53     142 1916.24
   143.9 1917.14   148.5 1920.27   150.8 1921.35   153.7 1922.59   160.4 1924.57
#Mann= 3 ,-1,0
       0      .1       0   109.7    .045       0   118.8      .1       0
#XS Ineff= 2 , 0
           56.63 1917.81
Permanent Ineff=
       F       F
Bank Sta=109.7,118.8
XS Rating Curve= 0 ,0
Exp/Cntr(USF)=0,0
Exp/Cntr=0.3,0.1

Type RM Length L Ch R = 1 ,522     ,135.1,160.7,184.8
XS GIS Cut Line= 2
 2197891.8637534648422.519072409 2197908.6848454648557.760652112
#Sta/Elev= 30
       0  1919.4     2.7 1919.66     6.7 1919.78    13.4 1919.61    18.8 1919.36
    26.9 1918.08    34.9 1915.97      39 1915.56      47 1915.59    51.1 1915.42
    55.1 1915.06      60 1914.34    67.2 1913.65    71.2 1913.49    74.4 1913.61
    79.3 1913.54    86.51911.808    87.3 1911.63    91.4 1911.41    94.61911.803
    99.5 1912.47   103.5 1912.64   107.5 1913.36   111.5 1915.26   115.5 1918.18
   119.6 1920.95   123.6 1923.46   131.7 1928.29   135.3 1929.46   136.3 1929.72
#Mann= 3 ,-1,0
       0      .1       0    86.5    .045       0    94.6      .1       0
Bank Sta=86.5,94.6
XS Rating Curve= 0 ,0
Exp/Cntr(USF)=0,0
Exp/Cntr=0.3,0.1

Type RM Length L Ch R = 1 ,361     ,69.8,59.4,105.8
XS GIS Cut Line= 4
 2197874.8428901648425.9747671942197801.57768937 648512.69684152
2197672.24218197648630.8182875842197687.19426375648672.684116569
#Sta/Elev= 30
       0 1917.76    12.7 1917.44    28.9 1916.49    53.7  1916.4    72.3 1915.28
    82.7 1915.57    98.4 1915.35   120.8 1912.22   126.1 1911.94   140.3 1912.59
   148.8 1912.62   155.8 1911.98   171.5 1911.52   173.6 1911.25   185.4  1911.1
   191.3 1911.22   193.51911.526   197.3  1911.6   199.8 1912.28     214 1914.02
   226.9 1914.96   236.6 1914.78   250.9 1915.04   288.7 1916.74   295.4 1918.38
   299.9 1920.55   312.4 1927.52   320.9 1931.34   325.7 1932.61   333.1 1933.75
#Mann= 3 ,-1,0
       0      .1       0   171.5    .045       0   193.5      .1       0
Bank Sta=171.5,193.5
XS Rating Curve= 0 ,0
Exp/Cntr(USF)=0,0
Exp/Cntr=0.3,0.1

Type RM Length L Ch R = 1 ,302     ,146,146,146
XS GIS Cut Line= 4
2197825.92549321648399.5544386892197765.12036064648487.937855434
 2197632.4621684648611.8739999692197638.27686687648646.263788064
#Sta/Elev= 30
       0 1916.83    11.7 1916.72    31.1 1918.15    40.8 1917.24    69.9  1917.7
    87.8 1917.23   120.1 1914.48   128.6 1914.43   138.4 1913.38   146.9 1912.89
   159.8 1912.89   173.9 1912.32   179.6 1912.45   185.3 1911.61   190.7 1910.18
   193.7 1909.92   201.6 1909.31   210.7 1909.92   223.5 1909.05   232.1 1908.93
   241.8  1909.6   256.4 1908.88   273.2 1909.19   283.7 1911.92   288.8 1911.83
   294.2 1913.92   300.1 1915.33   306.4 1915.77   317.5 1915.66   323.7 1916.87
#Mann= 3 ,-1,0
       0      .1       0   193.7    .045       0   210.7      .1       0
Bank Sta=193.7,210.7
XS Rating Curve= 0 ,0
Exp/Cntr(USF)=0,0
Exp/Cntr=0.3,0.1

Type RM Length L Ch R = 1 ,156     ,,,
XS GIS Cut Line= 4
2197743.09120209648427.3087633732197588.95554423648548.217572831
 2197561.2665039648605.4415895212197593.57038429648691.277614556
#Sta/Elev= 30
       0 1917.76     8.8 1917.16      19 1915.99    29.1  1914.5    39.3 1913.78
    74.9 1914.02    90.1 1913.93   100.3 1913.34   105.4 1913.29     197 1913.19
   232.5 1912.06   259.5 1910.64   276.3 1910.06   282.31907.398   284.8 1906.44
   289.5 1906.37   293.4 1906.57   295.7 1907.37   297.7 1908.28   301.9 1911.61
     305 1913.16   311.2 1915.15   314.8 1916.09     319 1916.62   327.6 1916.49
   331.8 1917.78   335.9  1920.5   345.4 1929.03   348.9 1931.76   351.2 1932.93
#Mann= 3 ,-1,0
       0      .1       0   282.3    .045       0   295.7      .1       0
Bank Sta=282.3,295.7
XS Rating Curve= 0 ,0
Exp/Cntr(USF)=0,0
Exp/Cntr=0.3,0.1
LCMann Table=0

Chan Stop Cuts=-1
Use User Specified Reach Order=0
Composite Channel Slope=5